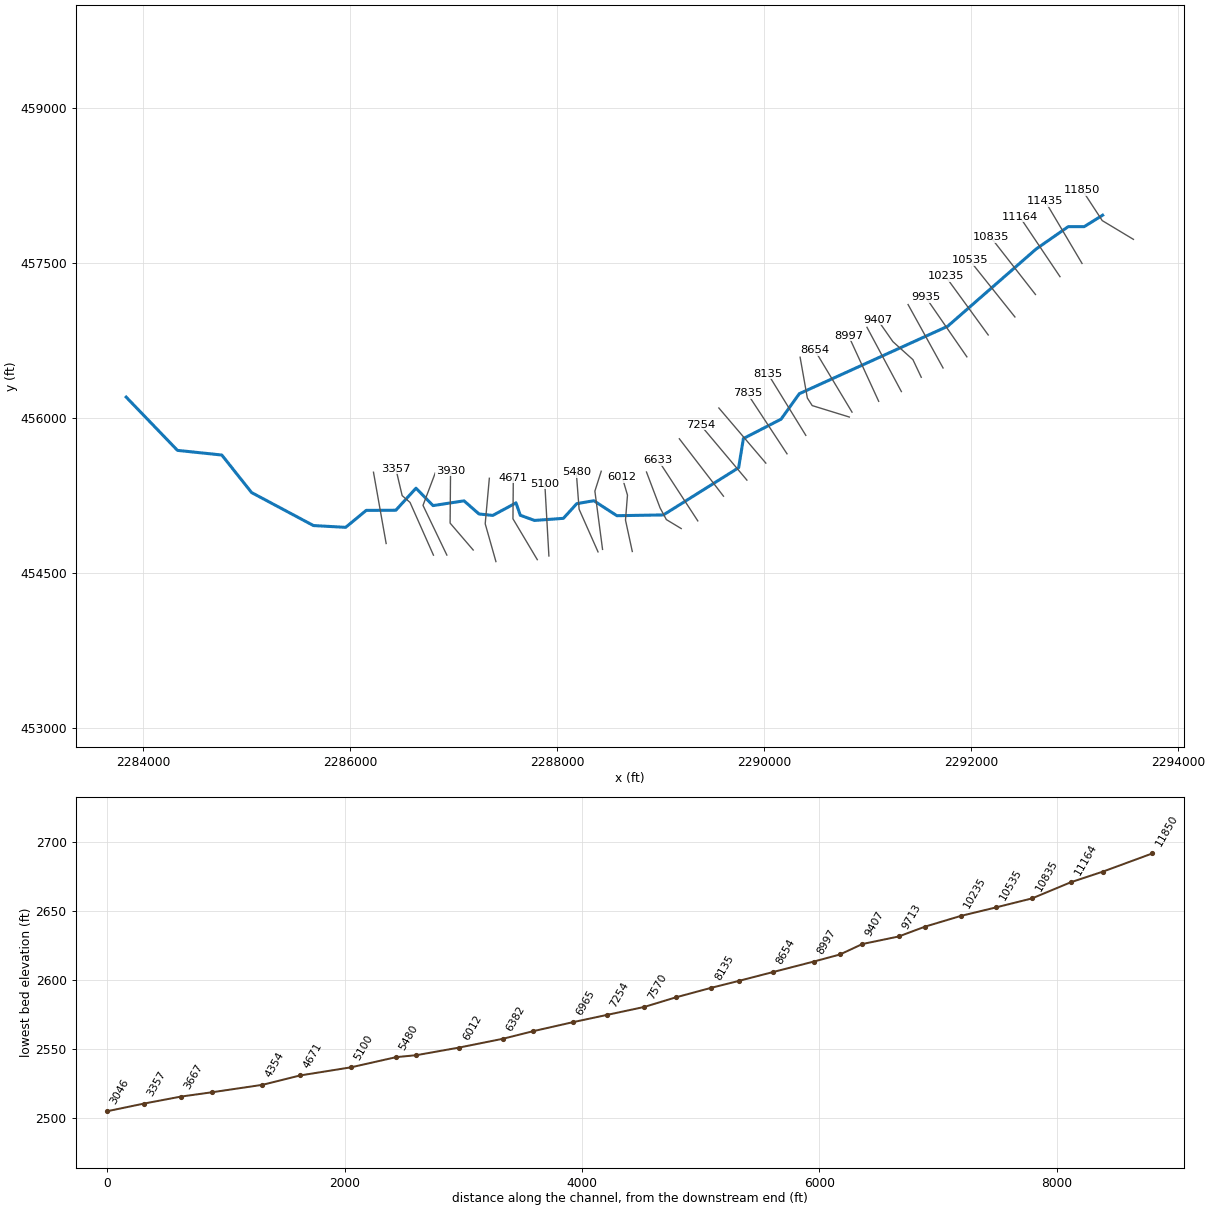
--- MOORERN2.prj (project) ---

Proj Title=MOORERN2
Current Plan=p01
Default Exp/Contr=0,0
English Units
Geom File=g01
Flow File=f01
Plan File=p01
Background Map Layer=Inundation Boundary (01pct Value_0)
BEGIN DESCRIPTION:
----------MODEL BY WOOD PLC 2021----------
Stream Name: Moore Run II
Flood Zone: Enhanced Approximate
Pocahontas County, WV
HEC-RAS Version: RAS 6.1
Vertical Datum: NAVD88
Projection: NAD 1983 StatePlane West Virginia S FIPS 4702 (US Feet)
Terrain: 1-meter LIDAR (FEMA Region III 3DEP collected 2016-2018)
Land Use: 2019 NLCD
Hydrologic Method:
WV SIR2010-5033 regression equations
Model Notes:
Normal depth tie in to KNAPPCK
END DESCRIPTION:
DSS File=dss
DSS Export Rating Curves= 0
DSS Export Rating Curve Sorted= 0
DSS Export Volume Flow Curves= 0
DXF OffsetX= 0
DXF OffsetY= 0
DXF ScaleX= 0
DXF ScaleY= 0

--- MOORERN2.p01 (plan) ---

Plan Title=Floodplain
Program Version=6.10
Short Identifier=Floodplain
Geom File=g01
Flow File=f01
Subcritical Flow
K Sum by GR= 0
Std Step Tol= 0.01
Critical Tol= 0.01
Num of Std Step Trials= 20
Max Error Tol= 0.3
Flow Tol Ratio= 0.001
Split Flow NTrial= 30
Split Flow Tol= 0.02
Split Flow Ratio= 0.02
Log Output Level= 0
Friction Slope Method= 1
Unsteady Friction Slope Method= 2
Unsteady Bridges Friction Slope Method= 1
Parabolic Critical Depth
Global Vel Dist= 0 , 0 , 0
Global Log Level= 0
CheckData=True
Encroach Param=-1 ,0,0, 0
Computation Interval=0.1SEC
Output Interval=1SEC
Instantaneous Interval=Max Profile
Mapping Interval=1HOUR
Computation Time Step Use Courant=        0
Computation Time Step Use Time Series=    0
Computation Time Step Count To Double=0
Computation Time Step Max Doubling=0
Computation Time Step Max Halving=0
Computation Time Step Residence Courant=0
Run HTab= 0
Run UNet= 0
Run Sediment= 0
Run PostProcess= 0
Run WQNet= 0
Run RASMapper=-1
UNET Theta= 0
UNET Theta Warmup= 0
UNET ZTol= 0
UNET ZSATol= 0
UNET MxIter= 0
UNET Max Iter WO Improvement= 0
UNET MaxInSteps= 0
UNET DtIC= 0
UNET DtMin= 0
UNET MaxCRTS= 0
UNET WFStab= 0
UNET SFStab= 0
UNET WFX= 1
UNET SFX= 1
UNET Gravity=32.174
UNET 1D Methodology=Finite Difference
UNET DSS MLevel= 1
UNET Pardiso=0
UNET DZMax Abort= 0
UNET Use Existing IB Tables= 0
UNET Froude Reduction=False
UNET Froude Limit= 0
UNET Froude Power= 0
UNET D1 Cores= 0
UNET WindReference=Eulerian
UNET WindDragFormulation=Hsu (1988)
UNET D2 Coriolis=0
UNET D2 Cores= 0
UNET D2 Theta= 1
UNET D2 Theta Warmup= 1
UNET D2 Z Tol= 0.01
UNET D2 Volume Tol= 0.01
UNET D2 Max Iterations= 20
UNET D2 Equation= 0
UNET D2 RampUpFraction=0.1
UNET D2 TimeSlices= 1
UNET D2 Turbulence Formulation=Non-Conservative (original)
UNET D2 Eddy Viscosity=0.3
UNET D2 Transverse Eddy Viscosity=0.1
UNET D2 Smagorinsky Mixing=0
UNET D2 BCVolumeCheck=0
UNET D2 Cores=0
UNET D2 SolverType=PARDISO (Direct)
UNET D2 Minimum Iterations= 2147483647
UNET D2 Maximum Iterations= 2147483647
UNET D2 Restart Number= 10
UNET D2 Relaxation Coeff=1.3
UNET D2 SOR Precondition Iterations= 10
UNET D2 ILUT Maximum Fill= 8
UNET D2 ILUT Tolerance=1E-08
UNET D1D2 MaxIter= 0
UNET D1D2 ZTol=0.01
UNET D1D2 QTol=0.1
UNET D1D2 MinQTol=1
DSS File=dss
Write IC File= 0
Write IC File at Fixed DateTime=0
Write IC File at Sim End=0
Echo Input=False
Echo Parameters=False
Echo Output=False
Write Detailed= 0
HDF Write Warmup=0
HDF Write Time Slices=0
HDF Flush=0
HDF Compression= 1
HDF Chunk Size= 1
HDF Spatial Parts= 1
HDF Use Max Rows=0
HDF Fixed Rows= 1
Calibration Method= 0
Calibration Iterations= 20
Calibration Max Change=0.05
Calibration Tolerance=0.2
Calibration Maximum=1.5
Calibration Minimum=0.5
Calibration Optimization Method= 1
WQ AD Non Conservative
WQ ULTIMATE=-1
WQ Max Comp Step=1HOUR
WQ Output Interval=15MIN
WQ Output Selected Increments= 0
WQ Output face flow=0
WQ Output face velocity=0
WQ Output face area=0
WQ Output face dispersion=0
WQ Output cell volume=0
WQ Output cell surface area=0
WQ Output cell continuity=0
WQ Output cumulative cell continuity=0
WQ Output face conc=0
WQ Output face dconc_dx=0
WQ Output face courant=0
WQ Output face peclet=0
WQ Output face adv mass=0
WQ Output face disp mass=0
WQ Output cell mass=0
WQ Output cell source sink temp=0
WQ Output nsm pathways=0
WQ Output nsm derived pathways=0
WQ Create Restart=0
WQ Fixed Restart=0
WQ System Summary=0
WQ Write To DSS=0
Sorting and Armoring Iterations= 10
XS Update Threshold= 0.02
Bed Roughness Predictor= 0
Hydraulics Update Threshold= 0.02
Energy Slope Method= 1
Volume Change Method= 1
Sediment Retention Method= 0
Sediment TS Multiplier= 1
Warm Up Method= 0
XS Weighting Method= 0
Number of US Weighted Cross Sections= 1
Number of DS Weighted Cross Sections= 1
Upstream XS Weight=0
Main XS Weight=1
Downstream XS Weight=0
Number of DS XS's Weighted with US Boundary= 1
Upstream Boundary Weight= 1
Weight of XSs Associated with US Boundary= 0
Number of US XS's Weighted with DS Boundary= 1
Downstream Boundary Weight= 0.5
Weight of XSs Associated with DS Boundary= 0.5
Percentile Method= 0
Sediment Output Level= 3
Mass or Volume Output= 0
Output Increment Type= 1
Profile and TS Output Increment= 1
Transport Output Increment 1
XS Output Flag= 0
XS Output Increment= 10
Read HDF5 Sediment Hotstart= 0
Sediment Hotstart Type= 0
Write Gradation File= 0
Read Gradation Hotstart= 0
Write HDF5 File= 1
Write Binary Output= 1
Write DSS Sediment File= 0
DSS Sediment Output Type= 1
SV Curve= 0
Specific Gage Flag= 0
Subcell Erosion Methods= 0
Subcell Deposition Methods= 0
Advection Scheme= 1
Matrix Solver= 0
Implicit Weighting Factor= 1
Maximum Outer Loop Convergence Iterations= 5
Convergence Maximum Absolute= 0.001
Convergence RMSE= 0.0001
Grain Fractions Max Abs Error= 0.001
Max Subgrid Regions= 1
Max Subgrid Length Scale= 3.402823E+38
Initial Layer Thickness= 3.402823E+38
Min Layer Thickness= 3.402823E+38
Max Layer Thickness= 3.402823E+38
Number of Layers= 5

--- MOORERN2.f01 (steady flow) ---

Flow Title=Flow
Program Version=6.10
Number of Profiles= 6
Profile Names=01pct,10pct,04pct,02pct,0_2pct,01plus
River Rch & RM=MOORERN2,Main,11850
     577     305     406     489     806     854
River Rch & RM=MOORERN2,Main,8366
     765     409     540     649    1060    1130
River Rch & RM=MOORERN2,Main,6382
     996     538     708     847    1380    1470
Boundary for River Rch & Prof#=MOORERN2,Main            , 1
Up Type= 0
Dn Type= 3
Dn Slope=0.01367
Boundary for River Rch & Prof#=MOORERN2,Main            , 2
Up Type= 0
Dn Type= 3
Dn Slope=0.01367
Boundary for River Rch & Prof#=MOORERN2,Main            , 3
Up Type= 0
Dn Type= 3
Dn Slope=0.01367
Boundary for River Rch & Prof#=MOORERN2,Main            , 4
Up Type= 0
Dn Type= 3
Dn Slope=0.01367
Boundary for River Rch & Prof#=MOORERN2,Main            , 5
Up Type= 0
Dn Type= 3
Dn Slope=0.01367
Boundary for River Rch & Prof#=MOORERN2,Main            , 6
Up Type= 0
Dn Type= 3
Dn Slope=0.01367
DSS Import GetInterval= 0
DSS Import GetPeak= 0
DSS Import FillOption= 0

--- MOORERN2.g01 (geometry) ---

Geom Title=Geometry
Program Version=6.10

River Reach=MOORERN2        ,Main
Reach XY= 30
     2293268.926      457962.768     2293090.897      457852.243
     2292936.281      457852.237     2292624.812      457634.726
2291770.99001891456888.516978394     2290338.304       456236.76
     2290161.918      455990.575 2289798.0088457 455803.29490178
2289751.91816494455521.190984982     2289025.042      455064.708
     2288575.293      455057.281     2288352.741      455202.038
     2288187.962      455173.8222288059.14642683455031.845133058
 2287779.6714135455011.393066084      2287642.09      455061.669
     2287600.899      455181.2132287376.84775259455060.100502207
2287243.23140755455073.922882729      2287098.74      455200.979
2286799.26970937455154.882540068     2286634.697      455323.338
     2286439.678      455109.987     2286153.748      455108.668
2285954.78808037454944.584893564       2285643.7      454961.939
     2285046.167      455280.895     2284758.341      455643.892
     2284329.961      455688.922     2283834.133      456204.214

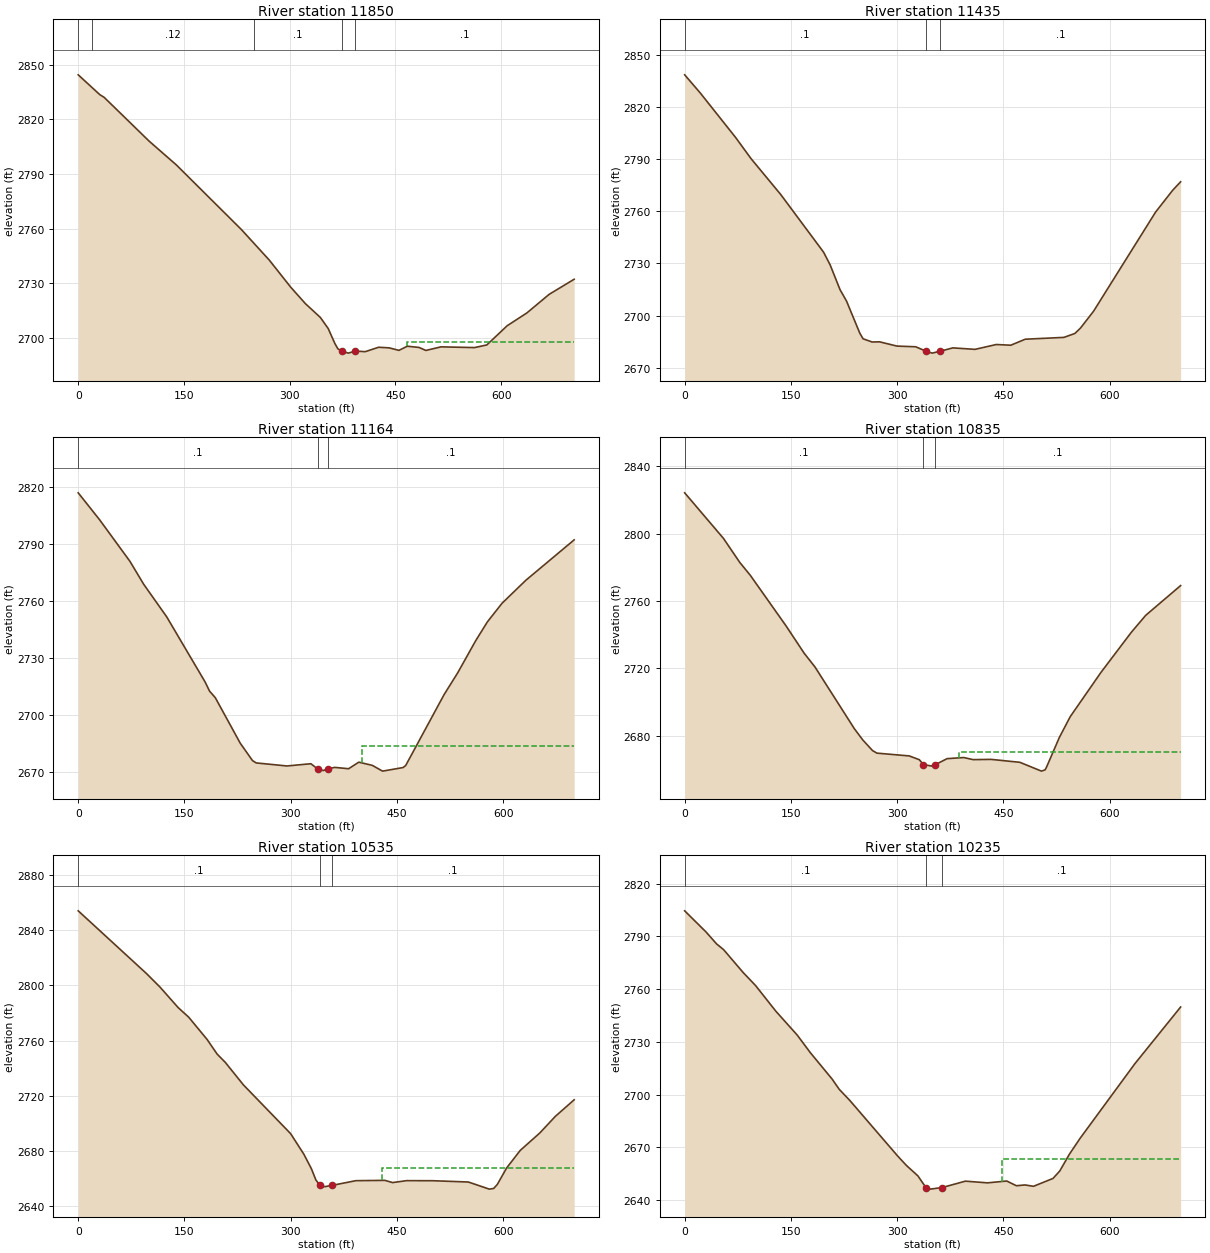
Type RM Length L Ch R = 1 ,11850   ,415,415,415
XS GIS Cut Line= 3
2293566.64986997457729.3414036852293265.46635616457910.474878261
2293072.74619815458205.376102744
#Sta/Elev= 30
       0 2844.56    30.7 2833.64    36.7 2832.22   100.9 2807.99   139.4 2794.96
   231.6 2759.45   271.3 2742.59   301.6 2727.74   322.3 2718.74   343.6 2711.12
   354.7 2705.05   364.2 2696.79   368.4  2693.9   373.8 2692.65   383.4  2691.5
   392.9 2692.66   407.2  2692.3   426.4 2694.74   441.6 2694.38     455 2693.01
     467  2695.3   483.7 2694.62   493.3 2692.97   514.7 2694.95   562.4 2694.55
   579.8    2696   608.6 2706.54   636.6  2713.6   668.2 2723.82   703.7 2732.13
#Mann= 5 ,-1,0
       0      .1       0      20     .12       0     250      .1       0
   373.8    .045       0   392.9      .1       0
#XS Ineff= 2 , 0
                             467         2697.53
Permanent Ineff=
       F       F
Bank Sta=373.8,392.9
XS Rating Curve= 0 ,0
Exp/Cntr(USF)=0,0
Exp/Cntr=0.3,0.1

Type RM Length L Ch R = 1 ,11435   ,270,271,271.8
XS GIS Cut Line= 2
2293070.02839923457496.5174144622292713.44726098458098.887642679
#Sta/Elev= 30
       0  2838.6    22.3 2828.01    71.9 2802.54    93.7 2790.34   135.6  2769.7
     196 2736.55   205.3 2729.23   219.2 2715.02   228.5 2708.32   247.1 2689.98
   251.8 2686.66   264.6 2684.81     275 2684.92   299.7 2682.46   326.2 2682.06
   340.1 2679.61   349.3 2678.41     361 2679.53   378.5 2681.43   409.8 2680.58
   439.8 2683.37   460.3 2682.96   480.7 2686.42   535.3 2687.47   550.8 2689.75
   558.6  2692.8   577.2 2702.57   664.6 2759.55   688.7 2772.11     700 2777.03
#Mann= 3 ,-1,0
       0      .1       0   340.1    .045       0     361      .1       0
Bank Sta=340.1,361
XS Rating Curve= 0 ,0
Exp/Cntr(USF)=0,0
Exp/Cntr=0.3,0.1

Type RM Length L Ch R = 1 ,11164   ,327,329,329.3
XS GIS Cut Line= 2
2292856.99663123457368.5825620572292466.69804706457949.673790002
#Sta/Elev= 30
       0 2817.03    30.2 2802.87      73 2781.02    92.3 2769.02     125 2751.77
     179 2717.65   185.5 2712.71   193.5 2709.32   228.7 2685.39     246 2676.24
   251.3 2675.01   294.6 2673.41   328.4 2674.59     338 2671.83   345.8 2671.02
     353 2671.92   362.1 2672.67   381.7 2671.96     396 2675.41   415.1 2673.73
   429.6  2670.7   458.5 2672.58   462.2 2673.64   516.3 2710.85   535.6 2722.36
     561 2739.26   577.5 2749.16   598.2 2758.95   631.9 2771.08     700 2792.29
#Mann= 3 ,-1,0
       0      .1       0     338    .045       0     353      .1       0
#XS Ineff= 2 , 0
                          399.89          2684.1
Permanent Ineff=
       F       F
Bank Sta=338,353
XS Rating Curve= 0 ,0
Exp/Cntr(USF)=0,0
Exp/Cntr=0.3,0.1

Type RM Length L Ch R = 1 ,10835   ,299,300,299.3
XS GIS Cut Line= 2
2292620.05820635457196.175165484 2292189.4135618457748.031297206
#Sta/Elev= 30
       0  2824.3    54.8  2797.2    77.8 2782.93    92.6 2775.31   142.9 2745.36
   168.7 2728.97   183.9 2720.85   239.7 2684.03   251.4 2677.47   265.1 2671.18
   271.4 2669.64     317 2667.98   331.2 2665.73   336.9 2662.86   348.3 2661.99
     354 2662.83   370.4 2666.37   393.9 2667.02   407.2 2665.78   432.5 2665.93
   473.1 2664.19   503.6 2658.95   508.7 2659.71   510.8 2661.38   528.9 2679.01
   544.2 2691.31   587.7 2717.69   630.4 2741.43   650.7  2751.5     700 2769.19
#Mann= 3 ,-1,0
       0      .1       0   336.9    .045       0     354      .1       0
#XS Ineff= 2 , 0
                          386.93         2670.19
Permanent Ineff=
       F       F
Bank Sta=336.9,354
XS Rating Curve= 0 ,0
Exp/Cntr(USF)=0,0
Exp/Cntr=0.3,0.1

Type RM Length L Ch R = 1 ,10535   ,300,300,299.2
XS GIS Cut Line= 2
2292421.49299075456978.9337136042291984.72174958 457525.95371588
#Sta/Elev= 30
       0 2853.92    96.5 2808.46   115.5 2798.71   141.1 2783.88     156 2776.93
     182  2760.8   196.1 2750.24   207.5 2744.31   233.2 2727.95   299.8 2692.68
   318.5 2677.79   329.1 2667.32   335.5 2659.13   341.2 2655.31   348.3 2654.31
   358.3 2655.24   391.9 2658.63   432.8 2658.87   443.7 2657.26   463.6 2658.66
   500.6  2658.6   550.6 2657.67   580.3 2652.52   586.4    2653   591.5 2655.86
   604.7 2667.83   623.9 2680.55   651.5 2693.14   673.4 2705.15     700 2717.18
#Mann= 3 ,-1,0
       0      .1       0   341.2    .045       0   358.3      .1       0
#XS Ineff= 2 , 0
                          429.46         2667.83
Permanent Ineff=
       F       F
Bank Sta=341.2,358.3
XS Rating Curve= 0 ,0
Exp/Cntr(USF)=0,0
Exp/Cntr=0.3,0.1

Type RM Length L Ch R = 1 ,10235   ,299,300,299.2
XS GIS Cut Line= 2
 2292163.6035382456804.7960243052291751.82612884457370.869663637
#Sta/Elev= 30
       0 2804.49    30.2 2792.45      45 2785.69    54.9 2782.44    82.9 2769.27
   100.1    2762   128.7 2747.43   158.8 2733.89   177.4 2723.84   208.2 2708.81
   218.1 2703.05     233 2696.75   300.5 2665.17   312.8 2659.82   329.2 2653.82
   340.6 2647.11   346.7 2646.29   363.5  2647.2   396.2 2650.82   427.4 2649.86
   454.6  2650.9   468.2 2648.22   480.3 2648.67   492.4  2647.9   519.8 2652.35
   529.4 2656.58     543 2666.12   558.2 2675.22   635.5 2717.62     700 2749.81
#Mann= 3 ,-1,0
       0      .1       0   340.6    .045       0   363.5      .1       0
#XS Ineff= 2 , 0
                          447.21         2663.58
Permanent Ineff=
       F       F
Bank Sta=340.6,363.5
XS Rating Curve= 0 ,0
Exp/Cntr(USF)=0,0
Exp/Cntr=0.3,0.1

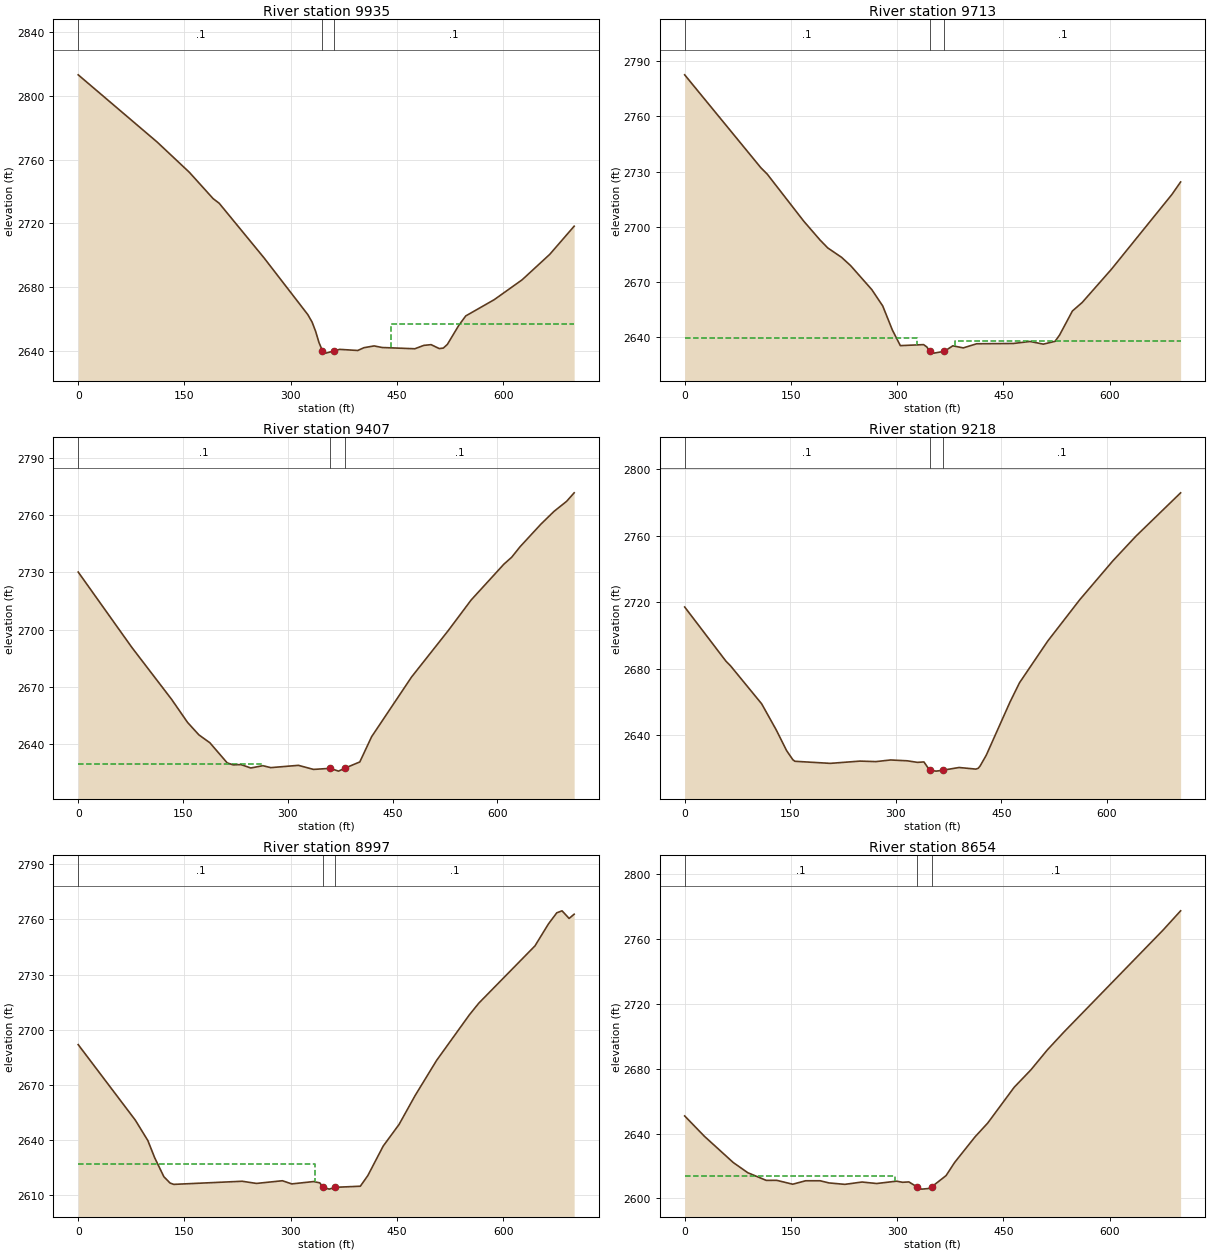
Type RM Length L Ch R = 1 ,9935    ,222.5,222.4,220.3
XS GIS Cut Line= 2
2291957.26972109456593.3964498472291559.72729972457169.556170077
#Sta/Elev= 30
       0 2813.11   111.5 2770.92   156.9 2751.97   190.4 2735.48     199 2732.56
   262.2 2698.36   324.1 2662.72   330.2 2657.97   335.1 2652.23   339.9 2645.13
   344.8 2639.97   349.6 2638.57   361.1 2639.95   369.1 2640.93   394.6 2640.23
   403.2 2641.96   417.6 2643.09   429.1 2642.09   475.1 2641.31   487.9 2643.44
   498.1 2643.88   509.6 2641.42   515.4 2641.75   521.1 2644.07   537.2    2656
     547  2661.9   587.3 2672.13   626.6 2684.57   665.5 2700.49     700 2718.17
#Mann= 3 ,-1,0
       0      .1       0   344.8    .045       0   361.1      .1       0
#XS Ineff= 2 , 0
                          441.86         2657.07
Permanent Ineff=
       F       F
Bank Sta=344.8,361.1
XS Rating Curve= 0 ,0
Exp/Cntr(USF)=0,0
Exp/Cntr=0.3,0.1

Type RM Length L Ch R = 1 ,9713    ,295,306,307.6
XS GIS Cut Line= 2
2291727.16517676456485.9274152092291389.19759727457098.934686954
#Sta/Elev= 30
       0 2782.62   107.6 2732.12   116.5  2728.7   168.1 2703.11     191 2692.92
   201.9 2688.61   221.6 2683.44   234.3 2678.95   264.1 2665.96   279.6 2657.03
   293.1 2644.05   304.4 2635.52   337.2 2636.07   341.7 2634.84   345.9 2632.44
     352 2631.45   366.7 2632.47   378.5 2635.43   393.2 2634.29   412.1 2636.53
   463.9 2636.69   487.5 2637.78   506.2 2636.33   522.8 2637.86     529 2641.18
   547.3 2654.35     561 2658.93   602.1  2676.9   687.7 2717.63     700 2724.42
#Mann= 3 ,-1,0
       0      .1       0   345.9    .045       0   366.7      .1       0
#XS Ineff= 2 , 0
          328.19 2639.84  381.01         2638.14
Permanent Ineff=
       F       F
Bank Sta=345.9,366.7
XS Rating Curve= 0 ,0
Exp/Cntr(USF)=0,0
Exp/Cntr=0.3,0.1

Type RM Length L Ch R = 1 ,9407    ,193.8,188.8,183.7
XS GIS Cut Line= 4
2291516.63408701456395.6845670882291436.14237408456566.010553568
2291242.55371966 456740.062738272291093.00629129456954.046012774
#Sta/Elev= 30
       0 2730.16    76.6 2690.81   133.7 2663.53   156.5 2651.48   172.7 2644.97
   188.4 2640.85   213.3 2630.28   221.8 2629.26   233.1  2629.4     247 2627.63
   264.3 2628.84   275.6 2627.82   315.2 2629.02   336.7 2626.89   360.6 2627.44
   360.6 2627.43   372.6 2625.99     382 2627.59     403 2630.79     420 2644.04
   477.1 2675.24   529.7 2699.57   562.3  2715.5   609.2 2734.26   620.5 2737.94
   632.2 2743.32   662.3 2755.25     681 2761.91     699 2767.16   709.8 2771.61
#Mann= 3 ,-1,0
       0      .1       0   360.6    .045       0     382      .1       0
#XS Ineff= 2 , 0
          265.03 2629.55
Permanent Ineff=
       F       F
Bank Sta=360.6,382
XS Rating Curve= 0 ,0
Exp/Cntr(USF)=0,0
Exp/Cntr=0.3,0.1

Type RM Length L Ch R = 1 ,9218    ,221.2,221.1,219.7
XS GIS Cut Line= 2
2291324.43772093456257.4156926432290991.99392575456878.895016761
#Sta/Elev= 30
       0 2717.17    58.7 2684.55      65 2681.86   109.4 2658.93   130.1 2643.24
   144.8  2630.8   153.7  2625.3   156.7 2624.35   206.9  2623.1   249.2 2624.46
   271.9 2624.16   292.6 2625.14   316.2 2624.64   330.9  2623.7     340 2623.96
   348.3  2618.9   357.6 2618.43   366.5 2618.95   389.9 2620.61   413.8 2619.65
   417.1 2620.13   419.7 2621.41   428.6 2628.01   462.4 2660.05   475.8 2671.56
   515.7 2696.52   561.5 2721.57   608.8 2745.07   641.3 2759.78   704.8 2785.85
#Mann= 3 ,-1,0
       0      .1       0   348.3    .045       0   366.5      .1       0
Bank Sta=348.3,366.5
XS Rating Curve= 0 ,0
Exp/Cntr(USF)=0,0
Exp/Cntr=0.3,0.1

Type RM Length L Ch R = 1 ,8997    ,340.5,342.8,343.3
XS GIS Cut Line= 2
2291105.21110558456163.3164841532290813.02214041456799.418369571
#Sta/Elev= 30
       0 2691.87    80.6 2650.82    98.3 2639.71   107.9 2630.42   120.9 2620.06
   129.7  2616.6   134.9 2615.89   231.4 2617.59   251.6 2616.41   288.2 2617.87
   301.4 2616.15   332.2 2617.42     341 2616.72   345.4 2614.33   354.2 2613.31
     363  2614.3   398.2 2614.89   408.8 2620.69   430.5 2636.73   452.9  2648.5
   475.7  2664.3   505.9 2683.33   552.3 2708.17   565.5 2714.45   644.7 2745.56
   663.7 2757.49   675.5 2763.54   682.9 2764.62   692.9 2760.49     700 2762.77
#Mann= 3 ,-1,0
       0      .1       0   345.4    .045       0     363      .1       0
#XS Ineff= 2 , 0
          334.42 2626.72
Permanent Ineff=
       F       F
Bank Sta=345.4,363
XS Rating Curve= 0 ,0
Exp/Cntr(USF)=0,0
Exp/Cntr=0.3,0.1

Type RM Length L Ch R = 1 ,8654    ,292.5,287.8,281
XS GIS Cut Line= 2
2290847.68603587456058.4855994192290487.26102083456658.563768101
#Sta/Elev= 30
       0 2650.86    27.8 2638.33    68.5 2622.16    89.1 2615.85   115.1 2611.14
   129.9 2611.16   152.5 2608.77   170.7  2610.9   191.1  2610.9   203.8 2609.56
   226.1 2608.68   250.4 2610.12     271  2609.2     299 2610.64   307.7 2609.95
   316.4  2610.2   328.1 2607.08   334.4 2605.74   343.8 2606.08   348.6 2607.12
   368.9 2614.06   381.1 2622.22   409.7  2637.9   427.8 2646.51   465.1 2668.54
   488.5 2679.18   511.7 2691.47   535.1  2702.5   675.1 2765.38     700 2777.31
#Mann= 3 ,-1,0
       0      .1       0   328.1    .045       0   348.6      .1       0
#XS Ineff= 2 , 0
           297.4 2613.64
Permanent Ineff=
       F       F
Bank Sta=328.1,348.6
XS Rating Curve= 0 ,0
Exp/Cntr(USF)=0,0
Exp/Cntr=0.3,0.1

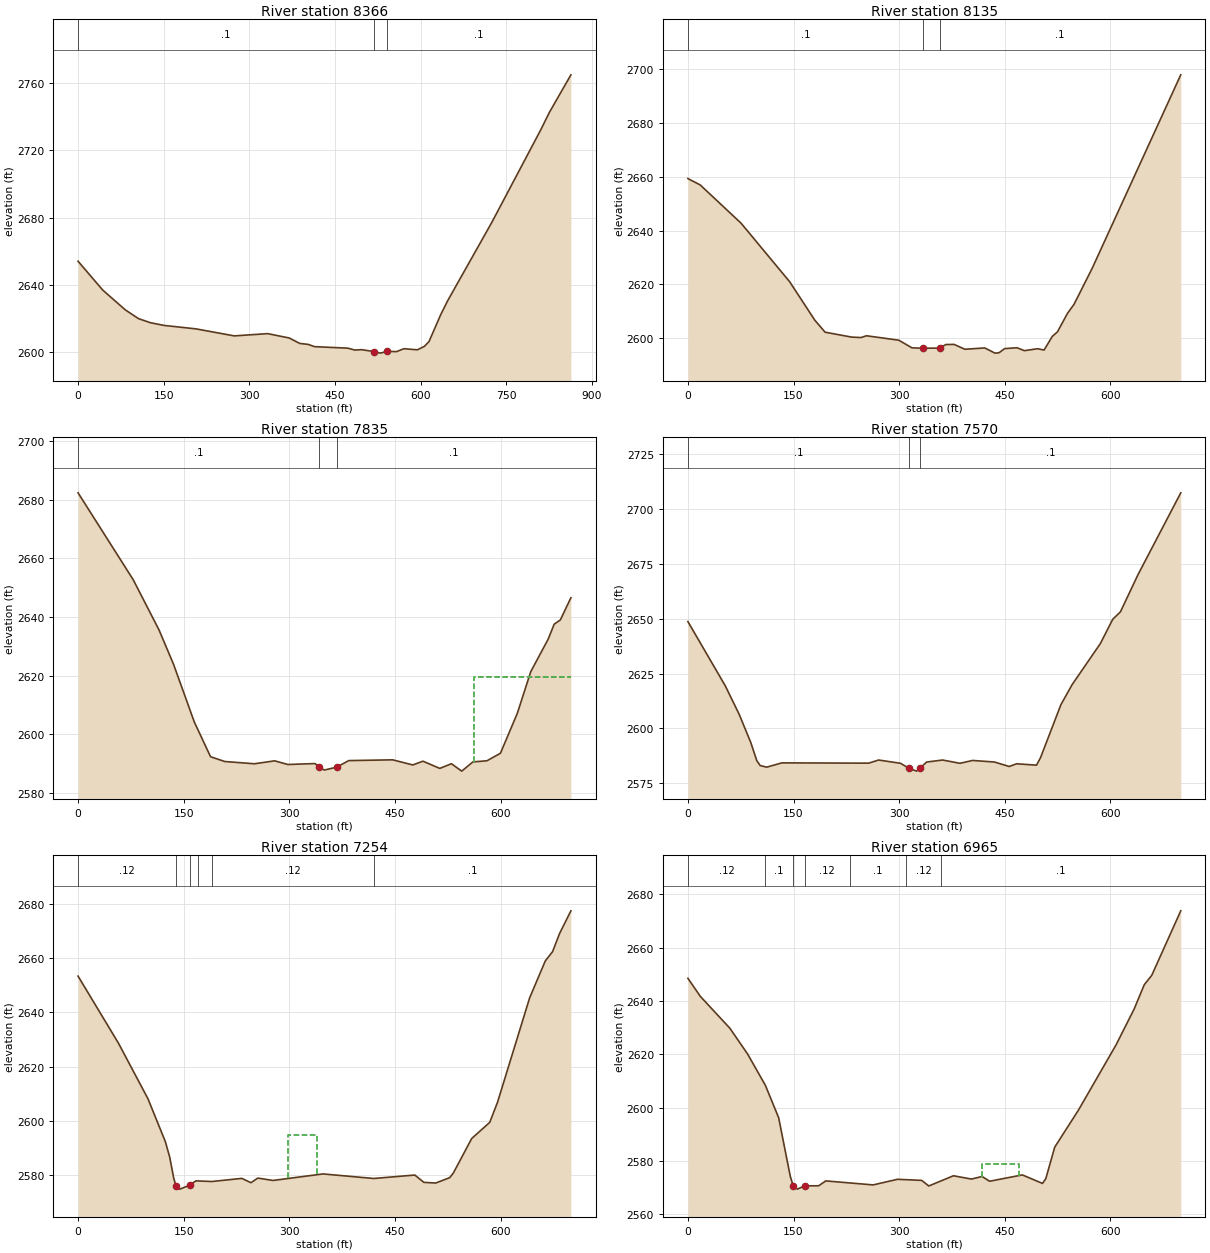
Type RM Length L Ch R = 1 ,8366    ,225.3,231.2,237.1
XS GIS Cut Line= 4
2290821.36948595456011.221379255 2290462.8709739456121.999878305
2290415.88215825456195.2639286092290345.97588819456589.723313047
#Sta/Elev= 30
       0 2654.02    43.1 2636.91    82.5 2625.15   105.9 2619.86   126.8 2617.44
   150.3 2615.85   206.4 2613.78   273.4 2609.61     332 2610.94   369.7 2608.36
   388.2 2605.12   402.8 2604.55   414.2  2603.2   472.3 2602.31   484.7 2601.17
   496.7 2601.41   518.9 2600.22   529.2 2599.35   541.4  2600.4   557.6 2600.25
   570.6 2601.97   594.2 2601.33   606.4 2603.38   614.5 2606.26   634.8 2622.11
     647 2630.44   724.2    2677   809.5 2731.81   825.4 2742.68   862.9 2764.93
#Mann= 3 ,-1,0
       0      .1       0   518.9    .045       0   541.4      .1       0
Bank Sta=518.9,541.4
XS Rating Curve= 0 ,0
Exp/Cntr(USF)=0,0
Exp/Cntr=0.3,0.1

Type RM Length L Ch R = 1 ,8135    ,295.7,300,297.9
XS GIS Cut Line= 2
  2290401.036649455834.0807197462290034.30376522456430.324790536
#Sta/Elev= 30
       0 2659.33    17.4 2656.98    75.6  2642.7   144.5 2620.95   180.2 2606.65
   194.8 2602.17   232.6 2600.34     246 2600.18   253.6 2600.84   299.5 2599.19
   318.3 2596.34   334.4 2596.21   357.6 2596.26   366.3 2597.58     378 2597.63
   393.4 2595.82   421.6 2596.31   436.1 2594.38   441.9 2594.52   449.8 2596.06
   467.4 2596.38   477.9  2595.3   496.7 2596.02   505.9 2595.53   517.5  2600.6
   524.9 2602.31     539 2609.14   548.4 2612.54   574.3 2626.01     700 2697.94
#Mann= 3 ,-1,0
       0      .1       0   334.4    .045       0   357.6      .1       0
Bank Sta=334.4,357.6
XS Rating Curve= 0 ,0
Exp/Cntr(USF)=0,0
Exp/Cntr=0.3,0.1

Type RM Length L Ch R = 1 ,7835    ,262.6,264.6,265.2
XS GIS Cut Line= 2
2290219.35858791455655.7752845812289835.02695246456240.830148669
#Sta/Elev= 30
       0 2682.33    78.3 2652.72   115.1 2635.54   135.7 2623.82   165.1 2604.21
   188.2 2592.35   208.4 2590.72   250.5 2589.95   279.3 2590.95   297.9  2589.7
   336.7 2590.02   342.5 2588.76   349.9 2587.81   367.3 2588.79   384.5 2591.03
   446.8 2591.29   475.5 2589.55   489.8 2590.83   513.8 2588.37   530.3 2589.97
   544.9 2587.44   560.8 2590.58   580.8 2590.97   599.9 2593.53   623.8  2607.1
     643 2621.36   667.7 2632.43   676.3 2637.56     685 2638.99     700 2646.56
#Mann= 3 ,-1,0
       0      .1       0   342.5    .045       0   367.3      .1       0
#XS Ineff= 2 , 0
                          562.79         2619.59
Permanent Ineff=
       F       F
Bank Sta=342.5,367.3
XS Rating Curve= 0 ,0
Exp/Cntr(USF)=0,0
Exp/Cntr=0.3,0.1

Type RM Length L Ch R = 1 ,7570    ,312.7,316.6,309.8
XS GIS Cut Line= 2
2290014.68430374 455565.780039272289560.84378805456098.723550644
#Sta/Elev= 30
       0 2648.66    53.2 2619.32    72.8 2606.41    89.3 2593.56    97.8 2585.31
   102.6 2583.08     112 2582.34   133.4 2584.29   256.7 2584.16   270.9 2585.59
   302.1 2584.09   313.5 2581.89   324.8 2580.53   330.2 2582.04     339 2584.67
   361.7 2585.59   386.4 2584.09   404.3 2585.39   435.3 2584.69   456.3 2582.64
   466.8 2583.88   495.1 2583.25   500.8 2586.65   529.8 2610.84   545.6  2619.9
   585.9 2638.72   603.4 2649.74   614.3 2653.12   639.3 2670.09     700 2707.35
#Mann= 3 ,-1,0
       0      .1       0   313.5    .045       0   330.2      .1       0
Bank Sta=313.5,330.2
XS Rating Curve= 0 ,0
Exp/Cntr(USF)=0,0
Exp/Cntr=0.3,0.1

Type RM Length L Ch R = 1 ,7254    ,287.4,288.3,285.1
XS GIS Cut Line= 2
2289831.94850368455401.2003530772289381.53651881455937.044587798
#Sta/Elev= 30
       0 2653.39    57.5 2628.57    99.3  2608.1     124 2592.26   130.2 2586.54
   135.8  2578.9   138.9 2576.06   144.6 2574.73   158.8 2576.21   167.3 2577.78
     190 2577.54   232.6  2578.7   245.6  2577.1   255.3 2578.81   276.9 2577.93
   347.8 2580.34     420 2578.66   478.3 2579.93   491.2 2577.23     508 2576.98
   527.9 2578.97     533 2580.66   559.1 2593.42   584.7 2599.38   595.7 2606.75
   641.4 2645.37   663.6 2658.98     674 2662.44     684 2669.18     700  2677.5
#Mann= 6 ,-1,0
       0     .12       0   138.9    .045       0   158.8     .12       0
     170      .1       0     190     .12       0     420      .1       0
#XS Ineff= 1 ,-1
  298.84  339.53 2594.54
Permanent Ineff=
       F
Bank Sta=138.9,158.8
XS Rating Curve= 0 ,0
Exp/Cntr(USF)=0,0
Exp/Cntr=0.3,0.1

Type RM Length L Ch R = 1 ,6965    ,333.3,332.7,330.7
XS GIS Cut Line= 2
2289605.63840298455245.9023242152289179.07048352455800.915666477
#Sta/Elev= 30
       0 2648.48    17.6 2641.72    59.6 2629.76    84.9 2620.05   110.1 2608.32
   128.9  2596.2   145.4 2574.23  149.41 2570.78   155.5 2569.45   165.6 2570.68
   185.7  2570.7   195.8 2572.53     263 2571.03   297.8 2573.14   332.1 2572.72
   342.1 2570.63   377.1 2574.46   402.7 2573.22   417.8  2574.2   428.4  2572.4
     475 2574.78   503.6 2571.59   508.3 2573.37     521  2585.2   554.9 2599.17
   608.1 2623.53   633.8 2636.98   648.1 2646.06   658.8 2649.61     700 2673.78
#Mann= 7 ,-1,0
       0     .12       0     110      .1       0  149.41    .045       0
   165.6     .12       0     230      .1       0     310     .12       0
     360      .1       0
#XS Ineff= 1 ,-1
  417.44  469.77 2579.02
Permanent Ineff=
       F
Bank Sta=149.41,165.6
XS Rating Curve= 0 ,0
Exp/Cntr(USF)=0,0
Exp/Cntr=0.3,0.1

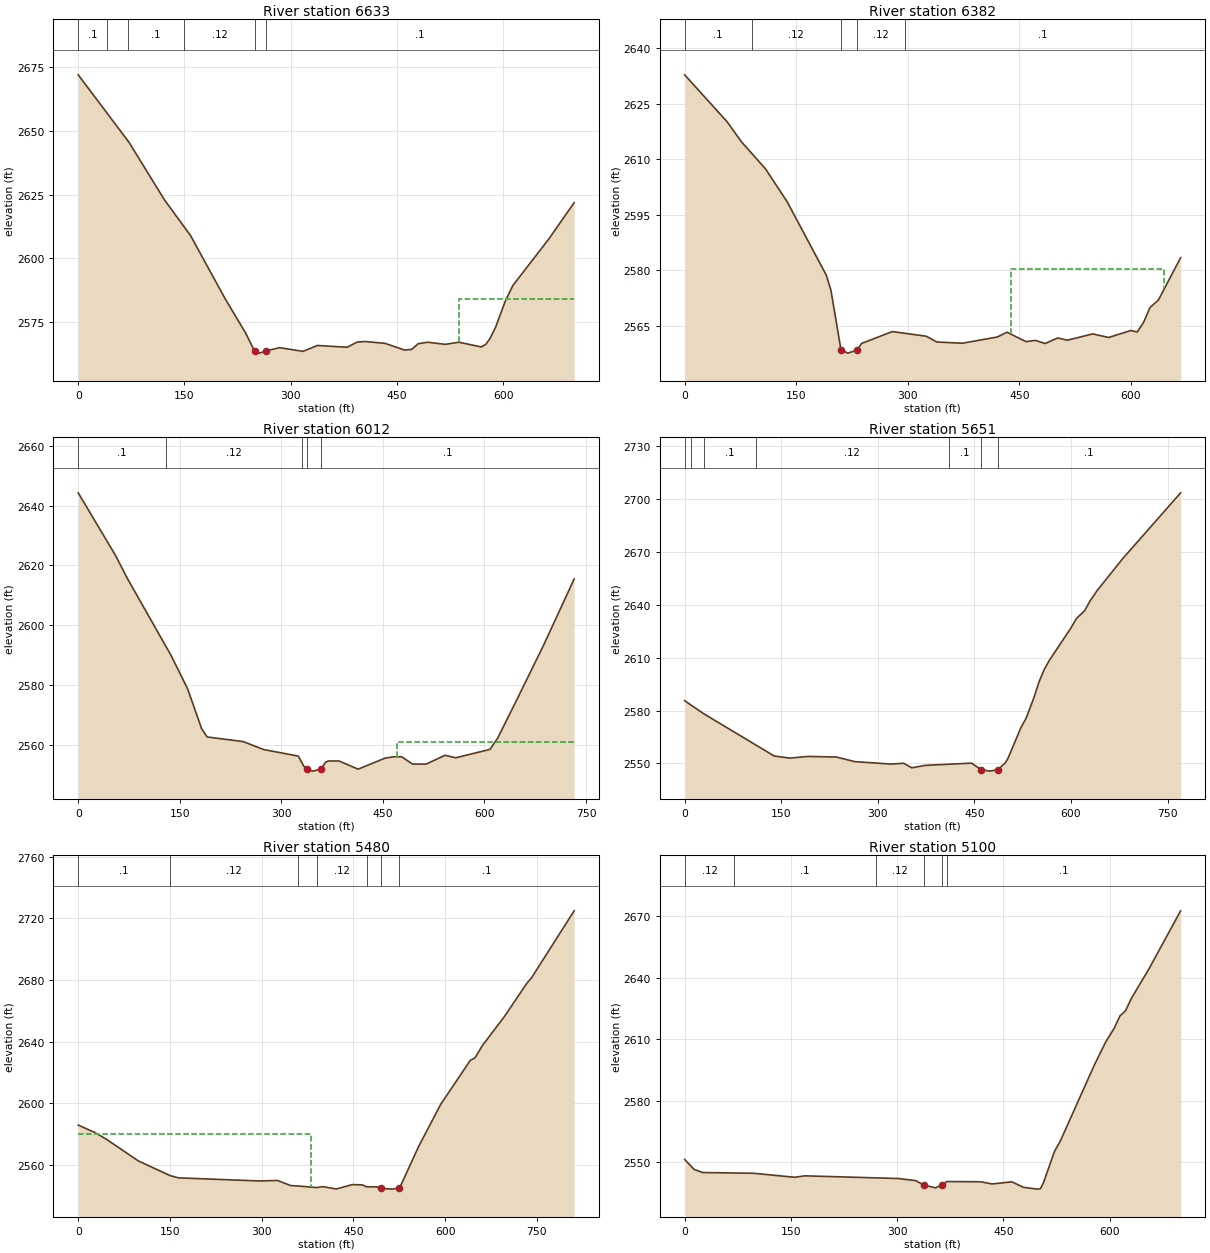
Type RM Length L Ch R = 1 ,6633    ,252,251.1,248.8
XS GIS Cut Line= 2
2289357.31838066455007.0719543282288975.32167933455593.654020344
#Sta/Elev= 30
       0 2671.79    71.7 2645.41   121.8 2622.88   158.5 2608.97   207.3 2584.29
   236.4  2570.8  248.88 2563.81   255.5 2562.98   265.1 2563.82   284.1 2565.12
   317.3 2563.68   337.7 2565.97   379.6 2565.28   393.9 2567.32   405.2 2567.52
   433.1 2566.79   460.8 2564.17   470.7 2564.45   479.9 2566.66   493.2 2567.24
     518 2566.41   537.2 2567.25     569 2565.39   575.3 2566.41   581.2 2568.66
   589.2 2573.16   603.1  2583.5   613.5 2589.42   664.4 2607.67     700 2621.81
#Mann= 6 ,-1,0
       0      .1       0      40     .12       0      70      .1       0
     150     .12       0  248.88    .045       0   265.1      .1       0
#XS Ineff= 2 , 0
                          537.21         2584.25
Permanent Ineff=
       F       F
Bank Sta=248.88,265.1
XS Rating Curve= 0 ,0
Exp/Cntr(USF)=0,0
Exp/Cntr=0.3,0.1

Type RM Length L Ch R = 1 ,6382    ,377.7,369.4,359.7
XS GIS Cut Line= 4
2289197.11952174 454932.954376182289053.62618573455019.574395651
2288992.99873531455132.6684484212288861.60695143455479.676716664
#Sta/Elev= 30
       0 2632.76    57.2 2620.05    76.6 2614.61   108.7 2607.36   137.8 2598.48
   190.6 2578.58   196.7 2574.56210.19962558.478   219.4 2557.57231.99932558.386
   237.8 2560.17   279.2 2563.39   324.9 2562.14   339.2 2560.58   373.5 2560.24
   420.5 2561.93   433.5 2563.22     459 2560.68   471.8 2561.01   484.7 2560.17
   501.8 2561.66   514.6 2561.06   548.8 2562.76   570.2  2561.8   600.2 2563.68
   608.7 2563.28   617.3 2565.91   625.8 2569.88   637.1 2571.91     667 2583.35
#Mann= 5 ,-1,0
       0      .1       0      90     .12       0210.1996    .045       0
231.9993     .12       0  295.93      .1       0
#XS Ineff= 1 ,-1
  438.37645.26312580.221
Permanent Ineff=
       F
Bank Sta=210.1996,231.9993
XS Rating Curve= 0 ,0
Exp/Cntr(USF)=0,0
Exp/Cntr=0.3,0.1

Type RM Length L Ch R = 1 ,6012    ,354,361.1,364.8
XS GIS Cut Line= 4
2288724.48580306454711.1230066082288658.81189328455014.779080358
2288677.99315445 455256.143283432288627.44760419455428.476696679
#Sta/Elev= 30
       0 2644.31    55.3 2623.29    72.7 2615.62   137.2 2589.87   161.7 2578.66
   182.2 2565.43   190.4 2562.62   243.6 2561.08   273.8 2558.41   325.1 2556.22
   333.1 2552.85     338 2551.93   346.7 2551.19   358.8  2551.9   365.2 2554.17
   369.3 2554.59   385.3 2554.58   413.4 2551.85   453.5 2555.56   465.6 2555.98
   477.6    2556   493.7 2553.56   513.7 2553.53   541.8 2556.49   557.5 2555.66
   608.1 2558.46   619.6 2562.29   649.8 2576.02   687.3 2593.34   732.4 2615.48
#Mann= 5 ,-1,0
       0      .1       0     130     .12       0  330.68      .1       0
     338    .045       0   358.8      .1       0
#XS Ineff= 2 , 0
                          470.99         2560.83
Permanent Ineff=
       F       F
Bank Sta=338,358.8
XS Rating Curve= 0 ,0
Exp/Cntr(USF)=0,0
Exp/Cntr=0.3,0.1

Type RM Length L Ch R = 1 ,5651    ,172.2,171,170
XS GIS Cut Line= 3
2288437.16117967454731.4066701572288363.04950558455294.655393208
2288424.45632125 455487.34574583
#Sta/Elev= 30
       0 2585.59      30 2578.12     139 2554.25   163.2 2553.06   191.4    2554
   235.8 2553.66     264 2551.06   320.5 2549.67   340.1 2550.14   352.8 2547.55
   373.3 2548.93   445.6 2550.21   460.22546.552   473.8 2545.67   486.42546.454
   498.2 2550.48   502.1 2552.83   522.2  2570.3   530.3 2575.63   542.4 2587.27
   550.5 2596.36   558.5 2603.32   566.6 2608.61   599.7 2626.69   608.5 2632.22
   621.1 2636.56   629.5 2642.07     641 2648.21   679.9 2665.96   770.3 2703.46
#Mann= 7 ,-1,0
       0      .1       0      10     .12       0      30      .1       0
     110     .12       0     410      .1       0   460.2    .045       0
   486.4      .1       0
Bank Sta=460.2,486.4
XS Rating Curve= 0 ,0
Exp/Cntr(USF)=0,0
Exp/Cntr=0.3,0.1

Type RM Length L Ch R = 1 ,5480    ,378.2,380.1,378
XS GIS Cut Line= 3
2288393.42876605454707.4459902262288210.75339761455119.371270762
2288183.16074164455478.617374386
#Sta/Elev= 30
       0 2585.81    28.1 2580.79    45.7  2576.7    98.2 2562.57   150.3 2552.99
   163.8 2551.56   295.1 2549.56   325.7 2549.84   347.8 2546.53     360 2546.26
   390.3 2545.25   400.1 2545.85     422 2544.33   447.9 2547.16   464.5 2546.99
   471.5 2545.75   488.5 2545.73   495.7 2544.76   512.6 2544.24   524.6 2544.86
   528.7 2547.74   556.7 2571.99   592.8 2599.29     641 2627.75     649 2629.48
     661 2637.45   696.9  2656.2   733.3 2677.63   741.3 2681.38   810.9 2724.78
#Mann= 7 ,-1,0
       0      .1       0   150.3     .12       0     360      .1       0
   390.3     .12       0   471.5      .1       0   495.7    .045       0
   524.6      .1       0
#XS Ineff= 2 , 0
             380    2580
Permanent Ineff=
       F       F
Bank Sta=495.7,524.6
XS Rating Curve= 0 ,0
Exp/Cntr(USF)=0,0
Exp/Cntr=0.3,0.1

Type RM Length L Ch R = 1 ,5100    ,420.5,429.5,422.3
XS GIS Cut Line= 2
2287918.73736398454667.8792854782287879.19721873455366.761662501
#Sta/Elev= 30
       0 2551.38    13.3 2546.52    25.3    2545    97.5 2544.62   155.3 2542.68
   169.6 2543.38   301.8 2542.07     326 2541.04   337.3 2538.95   353.9  2537.5
   363.9 2538.99   363.9    2539   369.9  2540.6     418 2540.47     434 2539.42
     462 2540.45   478.1 2537.78   498.1 2536.89   502.1 2537.07   506.1 2539.74
   522.1  2555.4   530.1 2560.29   578.2 2597.44   594.2 2608.68   606.3 2615.46
   614.4 2621.44   622.3 2624.02   630.3 2629.84   655.9 2644.77     700 2672.73
#Mann= 6 ,-1,0
       0     .12       0      70      .1       0     270     .12       0
   337.3    .045       0   363.9     .12       0     370      .1       0
Bank Sta=337.3,363.9
XS Rating Curve= 0 ,0
Exp/Cntr(USF)=0,0
Exp/Cntr=0.3,0.1

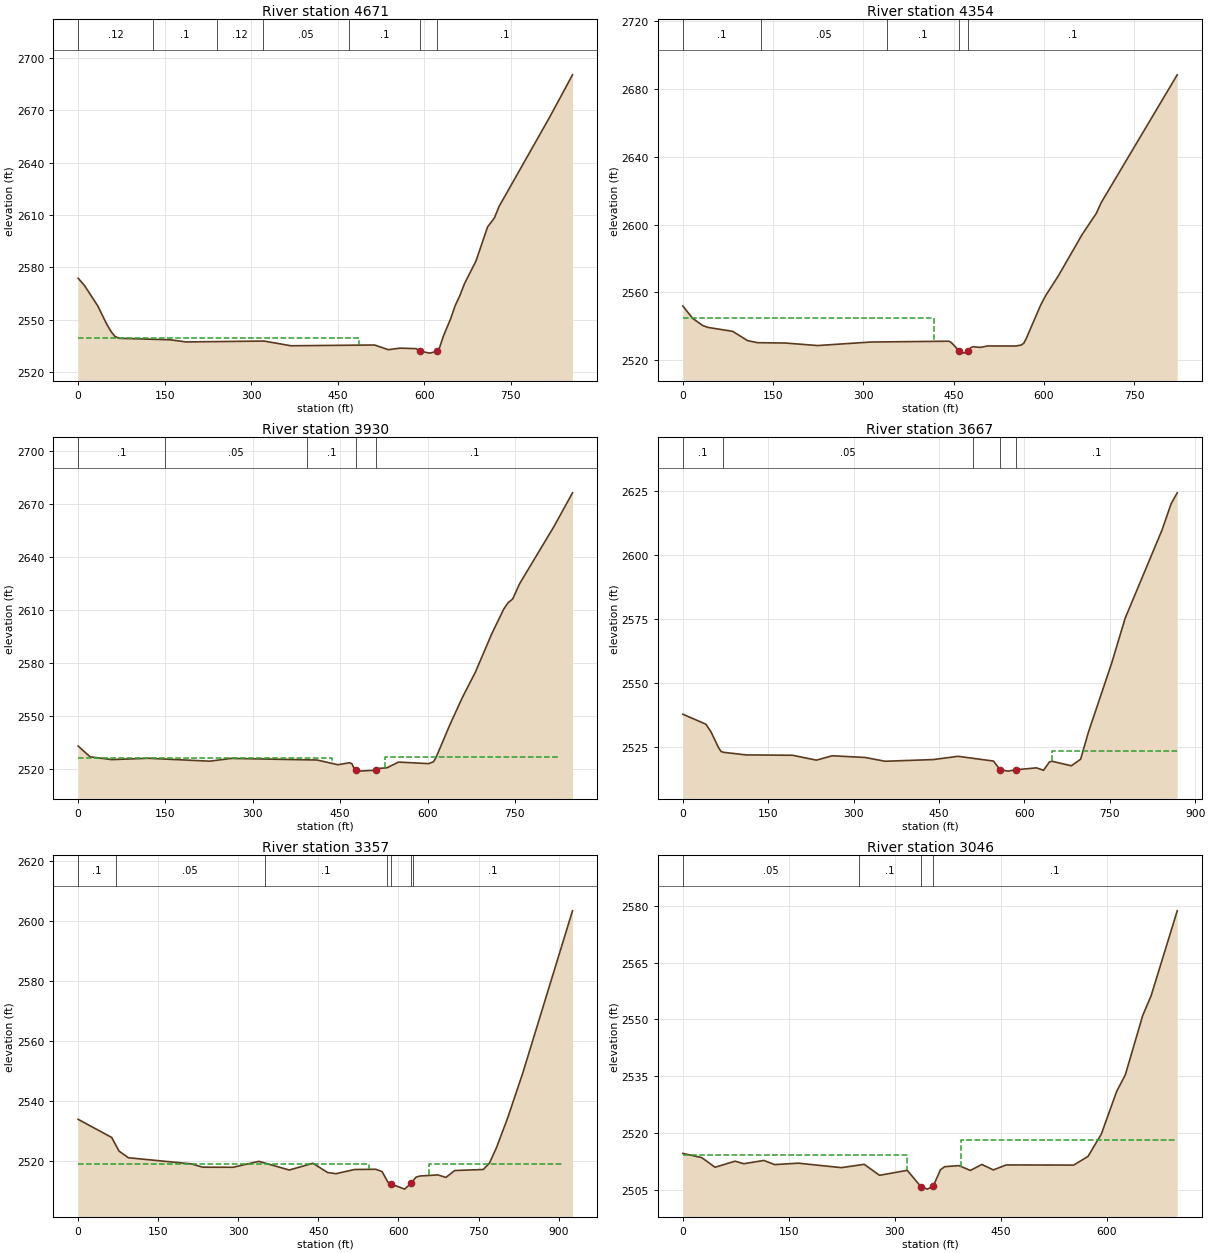
Type RM Length L Ch R = 1 ,4671    ,306.8,316.9,312.7
XS GIS Cut Line= 3
2287806.55727238454632.0874372142287571.51283634455027.186298523
2287574.88048352455424.413190573
#Sta/Elev= 30
       0 2573.81    10.6 2569.87    33.9  2558.1    49.2 2547.81    57.1 2543.36
    63.8 2540.55    71.1 2539.48   159.5 2538.63   187.4  2537.4   322.4  2537.9
     369 2535.21   513.7 2535.65   537.7 2532.97   557.9 2533.85   585.7 2533.58
593.36832532.056   609.7    2531621.76822532.039   626.5 2534.15   633.7 2541.16
   645.7 2550.59   653.7 2558.24   661.7 2563.86   669.7 2570.68   689.7 2583.69
   709.7 2603.09   721.7 2608.39   729.7 2614.86   817.7 2666.11     857 2690.14
#Mann= 7 ,-1,0
       0     .12       0     130      .1       0     240     .12       0
     320     .05       0  469.73      .1       0593.3683    .045       0
621.7682      .1       0
#XS Ineff= 2 , 0
          487.09 2539.63
Permanent Ineff=
       F       F
Bank Sta=593.3683,621.7682
XS Rating Curve= 0 ,0
Exp/Cntr(USF)=0,0
Exp/Cntr=0.3,0.1

Type RM Length L Ch R = 1 ,4354    ,418.3,423.3,420.8
XS GIS Cut Line= 3
2287406.86264086454613.5506980672287303.33038848454979.233145594
2287343.29706462455419.184003386
#Sta/Elev= 30
       0 2552.02    16.2 2544.76    32.9 2540.52    41.2 2539.44    82.8 2537.08
   107.7 2531.59   124.3 2530.39   170.1 2530.19   224.1  2528.7   312.9 2530.78
   442.3 2531.26   446.3 2530.46458.79022525.775   466.4 2524.23474.29012525.505
   478.4 2527.35   482.4 2528.04   494.5 2527.61   506.5 2528.45   553.6 2528.43
   562.8 2529.03   566.8 2530.13   570.4 2532.52   594.9 2552.67   603.5 2558.37
   624.3 2569.89     664 2594.34   687.3 2606.66   695.3  2612.9   821.8 2688.34
#Mann= 5 ,-1,0
       0      .1       0     130     .05       0     340      .1       0
458.7902    .045       0474.2901      .1       0
#XS Ineff= 2 , 0
           416.9 2545.15
Permanent Ineff=
       F       F
Bank Sta=458.7902,474.2901
XS Rating Curve= 0 ,0
Exp/Cntr(USF)=0,0
Exp/Cntr=0.3,0.1

Type RM Length L Ch R = 1 ,3930    ,269.1,263.5,260.3
XS GIS Cut Line= 3
2287187.27038138454725.5715980622286964.19606561454985.588980405
2286968.56466836455491.835391044
#Sta/Elev= 30
       0 2533.06    20.6 2526.97    57.5 2525.39   120.7 2526.13     226  2524.5
     263 2526.06   410.2 2525.16   446.2 2522.49   466.2 2523.62   470.2 2523.02
   474.2  2520.1     477 2519.45   482.2 2518.87   511.7  2519.4   518.2 2520.45
   530.2 2520.75   550.2 2523.98   602.2 2523.11   610.2  2524.2   614.2 2526.32
   638.2 2544.98   659.4 2560.25   682.2 2574.92   710.2  2596.5   730.8 2610.49
   738.2 2614.07   746.2 2616.27   758.2 2624.94   818.1 2657.81   848.9 2676.28
#Mann= 5 ,-1,0
       0      .1       0     150     .05       0  392.59      .1       0
     477    .045       0   511.7      .1       0
#XS Ineff= 2 ,-1
       0  435.45 2526.36   526.2  824.972527.079
Permanent Ineff=
       F       F
Bank Sta=477,511.7
XS Rating Curve= 0 ,0
Exp/Cntr(USF)=0,0
Exp/Cntr=0.3,0.1

Type RM Length L Ch R = 1 ,3667    ,282.7,310.2,327.5
XS GIS Cut Line= 3
2286932.60419867454676.6581813242286702.32325381455157.040100712
2286820.88983195455471.152380805
#Sta/Elev= 30
       0 2537.93    40.5 2534.02    49.4 2531.05    62.7 2524.87    67.1 2523.39
    71.6 2523.06   111.5 2522.04   192.6 2521.91   234.6 2520.01   262.3 2521.71
     320 2521.05   355.4 2519.57   439.7 2520.23   483.5  2521.5   545.7 2519.65
557.22162516.267   571.4 2515.72584.72162516.247   621.2    2517   633.6 2516.05
     644  2519.3   648.3 2519.58   682.5 2517.81   698.8 2520.37   712.4 2530.86
   753.2 2557.76     777 2575.36   841.6 2609.68   857.8 2620.05   868.5  2624.3
#Mann= 5 ,-1,0
       0      .1       0      70     .05       0     510      .1       0
557.2216    .045       0584.7216      .1       0
#XS Ineff= 2 , 0
                          647.93         2523.67
Permanent Ineff=
       F       F
Bank Sta=557.2216,584.7216
XS Rating Curve= 0 ,0
Exp/Cntr(USF)=0,0
Exp/Cntr=0.3,0.1

Type RM Length L Ch R = 1 ,3357    ,324.7,311.1,298.1
XS GIS Cut Line= 4
2286803.24161303454675.7838933892286577.08469371455185.543383112
2286500.92001151455251.3479681382286439.71251669455511.952707716
#Sta/Elev= 30
       0 2533.94    62.8 2527.91    76.6 2523.37    94.3 2521.14   211.6 2519.11
   233.5    2518   290.3 2517.97   338.5 2519.95   395.4 2517.06   439.9  2519.3
   467.2 2516.23   482.9 2515.83   517.9 2517.23   557.3 2517.31   569.4 2516.54
     580 2513.07586.07632512.405   611.7 2510.69623.31062512.614   632.9 2514.68
   640.3 2515.06   673.8 2515.43     689 2514.59   705.4 2516.89   758.8 2517.23
   770.3 2519.32   783.6 2524.49   804.8 2534.52   832.8 2549.33     926  2603.4
#Mann= 7 ,-1,0
       0      .1       0      70     .05       0     350      .1       0
  577.68     .05       0586.0763    .045       0623.3106     .05       0
  627.68      .1       0
#XS Ineff= 2 ,-1
       0  544.84 2519.19   656.9     909  2518.9
Permanent Ineff=
       F       F
Bank Sta=586.0763,623.3106
XS Rating Curve= 0 ,0
Exp/Cntr(USF)=0,0
Exp/Cntr=0.3,0.1

Type RM Length L Ch R = 1 ,3046    ,401.3,397.5,393.5
XS GIS Cut Line= 2
2286346.24031383454788.3291668542286223.88670728455477.553074567
#Sta/Elev= 30
       0 2514.57    26.7 2513.47    45.6 2510.92      74 2512.53    86.2 2511.85
   114.6 2512.72   130.2 2511.62   163.4    2512   224.3 2510.82   256.8 2511.69
   278.5 2508.79   317.7 2510.11   337.2 2505.77   346.2 2505.14   354.3 2505.87
   364.8 2510.26   370.6 2511.07   390.9 2511.35   407.1 2510.08   423.4 2511.66
   439.6 2510.22   457.9 2511.53   553.4 2511.49   573.7 2513.79   592.5 2519.67
   614.3 2530.99   626.5 2535.33   651.1 2550.99   663.1 2556.28     700 2578.67
#Mann= 4 ,-1,0
       0     .05       0     250      .1       0   337.2    .045       0
   354.3      .1       0
#XS Ineff= 2 , 0
          317.07 2514.15  393.97         2518.25
Permanent Ineff=
       F       F
Bank Sta=337.2,354.3
XS Rating Curve= 0 ,0
Exp/Cntr(USF)=0,0
Exp/Cntr=0.3,0.1