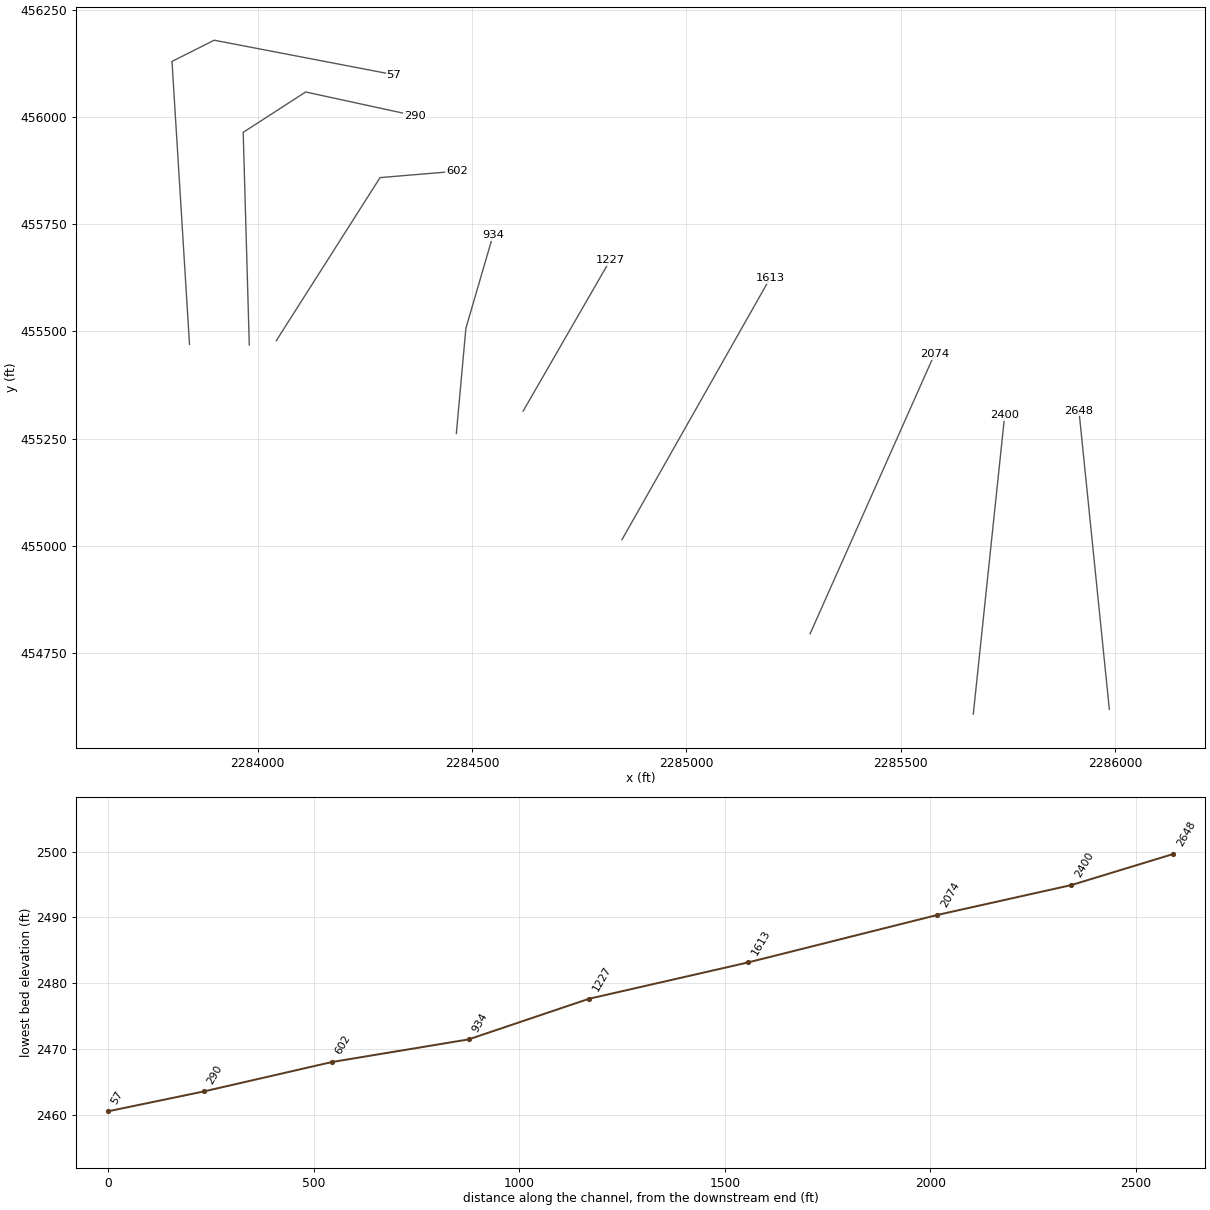
HEC-RAS study MOORERN2.prj: MOORERN2

--- MOORERN2.g01 (geometry) --- (continued)

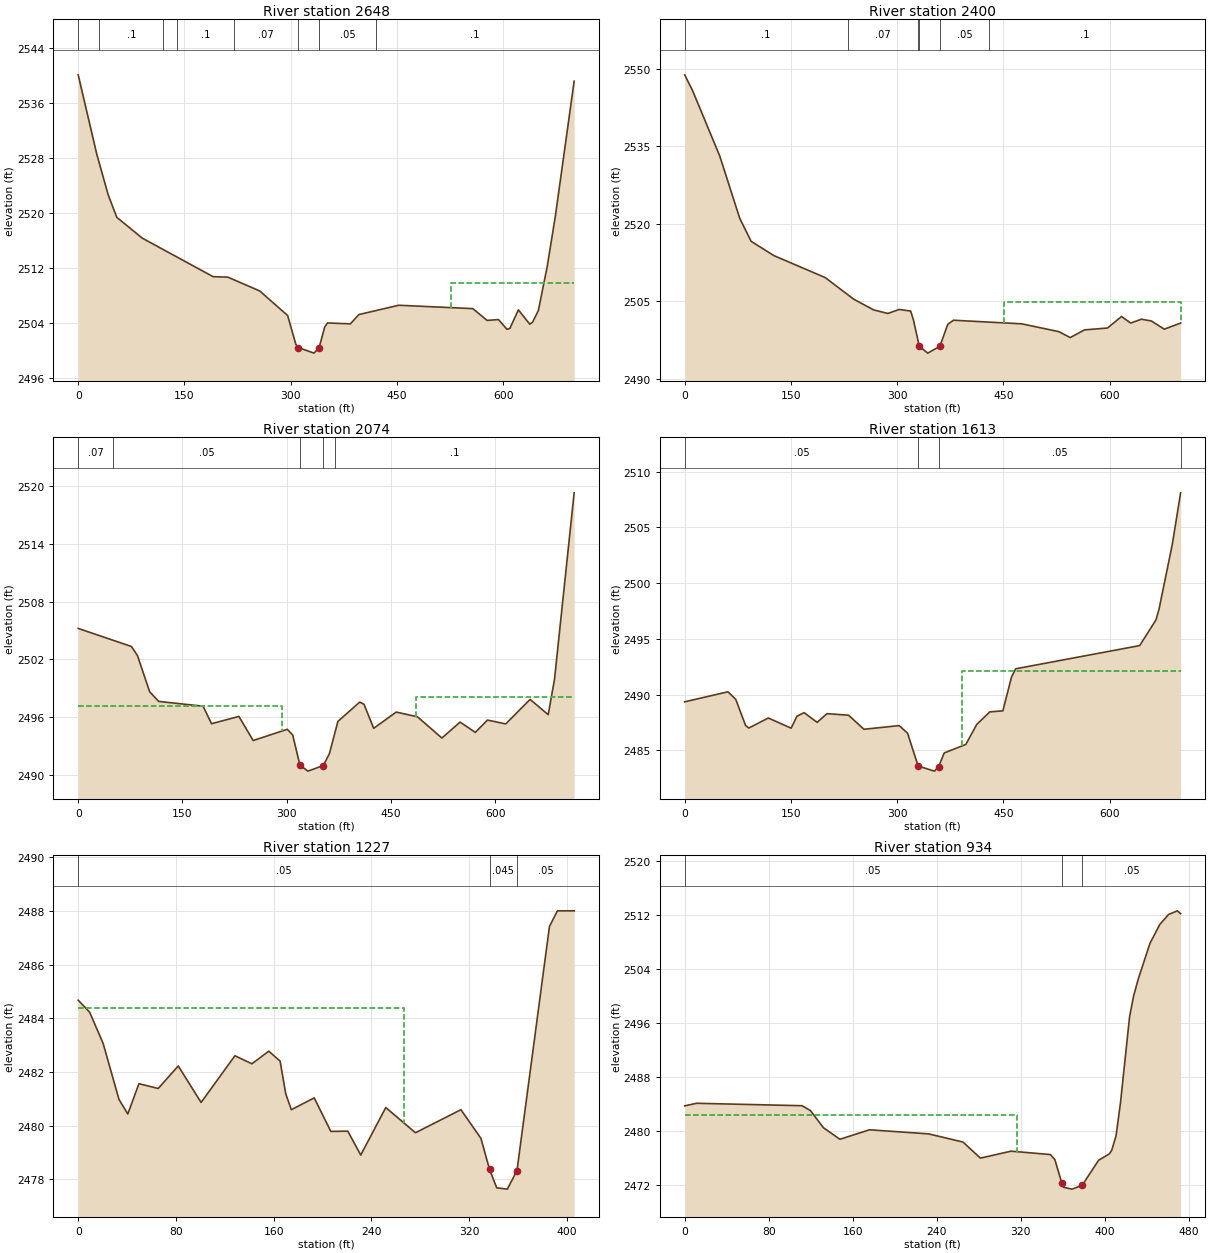
Type RM Length L Ch R = 1 ,2648    ,252.5,248,244.5
XS GIS Cut Line= 2
2285986.77910429454619.0613983042285915.86183648455315.459805199
#Sta/Elev= 30
       0 2540.06    26.3  2528.5    42.3 2522.65    54.4 2519.38    90.6 2516.34
   190.4 2510.76   211.2 2510.69   256.1 2508.69   295.6 2505.12   307.2 2500.93
   310.8 2500.47   332.7 2499.66     340 2500.43   347.9 2503.45   351.9 2504.04
   384.1 2503.91   396.2 2505.26   452.4 2506.61     557 2506.12   577.1 2504.41
   593.2 2504.53   605.2 2503.12   609.3 2503.25   621.3 2505.94   637.4 2503.86
   641.4 2504.17   649.5 2505.85     662 2512.24   673.6 2519.63     700 2539.14
#Mann= 8 ,-1,0
       0     .12       0      30      .1       0     120     .05       0
     140      .1       0     220     .07       0   310.8    .045       0
     340     .05       0     420      .1       0
#XS Ineff= 2 , 0
                          526.08         2509.85
Permanent Ineff=
       F       F
Bank Sta=310.8,340
XS Rating Curve= 0 ,0
Exp/Cntr(USF)=0,0
Exp/Cntr=0.3,0.1

Type RM Length L Ch R = 1 ,2400    ,333.2,326.2,321.7
XS GIS Cut Line= 2
2285669.48317693454607.9380844152285742.69290906455304.099226049
#Sta/Elev= 30
       0 2548.81    10.9 2545.84    49.5 2533.09    77.7 2521.04    93.8 2516.58
   125.9 2513.81   198.3 2509.56   238.5 2505.38   266.7  2503.3   286.8 2502.61
   302.9 2503.39     319 2503.07     323  2501.3   331.1 2496.28   331.1 2496.27
   343.1 2494.93   360.2 2496.25   371.3  2500.5   379.3  2501.3   475.9  2500.6
   528.1 2499.09   544.2 2497.94   564.3 2499.43   596.8 2499.79   616.6 2502.02
   629.5 2500.75   644.8  2501.5   658.7 2501.15   676.9 2499.57     700 2500.75
#Mann= 6 ,-1,0
       0      .1       0     230     .07       0     330     .05       0
   331.1    .045       0   360.2     .05       0     430      .1       0
#XS Ineff= 2 , 0
                          451.15          2504.8
Permanent Ineff=
       F       F
Bank Sta=331.1,360.2
XS Rating Curve= 0 ,0
Exp/Cntr(USF)=0,0
Exp/Cntr=0.3,0.1

Type RM Length L Ch R = 1 ,2074    ,461.8,460.7,457.9
XS GIS Cut Line= 2
2285288.93178062454795.2331227252285579.13821645455447.093139557
#Sta/Elev= 30
       0 2505.22    76.6 2503.34    85.3 2502.39   102.8 2498.63   115.8 2497.63
   179.7 2497.13   191.8 2495.31   231.2 2496.07   251.7 2493.56   300.8 2494.73
   308.6 2494.13     319    2491   330.5 2490.38   352.6 2490.96   361.4  2492.2
   373.6 2495.55     405 2497.56   411.2 2497.33   425.1 2494.83   457.5 2496.52
   488.1 2496.03   523.2 2493.82   549.4 2495.48   571.3 2494.41   588.8 2495.69
   615.1 2495.29   650.1 2497.84   676.2 2496.25   685.2 2499.91   713.5 2519.32
#Mann= 5 ,-1,0
       0     .07       0      50     .05       0     319    .045       0
   352.6     .05       0     370      .1       0
#XS Ineff= 2 , 0
          292.96 2497.14  486.31         2498.09
Permanent Ineff=
       F       F
Bank Sta=319,352.6
XS Rating Curve= 0 ,0
Exp/Cntr(USF)=0,0
Exp/Cntr=0.3,0.1

Type RM Length L Ch R = 1 ,1613    ,383.3,386.4,379.9
XS GIS Cut Line= 2
2284850.06960611 455014.481145482285195.23241023455623.466070294
#Sta/Elev= 30
       0 2489.36    61.1 2490.26    72.1 2489.58    85.9 2487.25    90.5 2487.01
     118 2487.91   150.3    2487   158.4 2488.07   168.6 2488.39     187 2487.52
   200.8  2488.3   231.4 2488.16     253  2486.9   302.8 2487.23   314.6 2486.55
   329.5 2483.61   352.5 2483.15   358.6 2483.56   366.3 2484.78   396.8 2485.54
   412.3 2487.34   430.7 2488.46   449.1 2488.55   461.3 2491.58   467.2 2492.32
   642.2  2494.4   665.2  2496.7   669.5 2497.66   688.2 2503.45     700 2508.09
#Mann= 4 ,-1,0
       0     .05       0   329.5    .045       0   358.6     .05       0
     700      .1       0
#XS Ineff= 2 , 0
                          391.86         2492.15
Permanent Ineff=
       F       F
Bank Sta=329.5,358.6
XS Rating Curve= 0 ,0
Exp/Cntr(USF)=0,0
Exp/Cntr=0.3,0.1

Type RM Length L Ch R = 1 ,1227    ,287.7,292.8,298.3
XS GIS Cut Line= 2
2284619.47593177455314.008438843 2284822.2556122455665.685087165
#Sta/Elev= 30
       0 2484.67     9.4 2484.22    20.4 2483.06    33.4 2480.97    40.6 2480.43
    49.7 2481.56    65.5 2481.38    81.9 2482.22   100.6 2480.86   128.3  2482.6
   142.2  2482.3     156 2482.77   165.3  2482.4   169.9 2481.18   174.5 2480.59
   193.2 2481.03   206.8 2479.78   220.7 2479.79   231.3  2478.9   251.8 2480.67
   276.1 2479.73   313.3 2480.59   329.7 2479.52   336.7 2478.37   342.6 2477.68
   351.3 2477.63   359.2 2478.32   385.8 2487.42   392.3    2488     406    2488
#Mann= 3 ,-1,0
       0     .05       0   336.7    .045       0   359.2     .05       0
#XS Ineff= 2 , 0
          266.61 2484.37
Permanent Ineff=
       F       F
Bank Sta=336.7,359.2
XS Rating Curve= 0 ,0
Exp/Cntr(USF)=0,0
Exp/Cntr=0.3,0.1

Type RM Length L Ch R = 1 ,934     ,336.4,332.2,328.8
XS GIS Cut Line= 3
2284463.75418797455261.8654320652284486.04999801455507.327370337
2284549.39308474455724.155628764
#Sta/Elev= 30
       0 2483.76    11.4 2484.14   111.8 2483.78   119.8 2483.06   132.3 2480.51
   147.9 2478.82     176 2480.22   232.3 2479.62   265.1 2478.41   281.7 2476.03
   310.8 2477.06   348.4 2476.56   352.6 2475.83   359.3  2472.3   360.9 2471.72
     369 2471.45   378.7 2472.03   394.3 2475.72   404.5 2476.66   406.8  2477.2
   410.9 2479.33   415.1 2484.19   423.8 2496.94   427.6 2499.99   431.8 2502.38
   443.2 2507.78   452.6 2510.58   460.9 2512.05   469.3 2512.59   472.4 2512.16
#Mann= 3 ,-1,0
       0     .05       0   359.3    .045       0   378.7     .05       0
#XS Ineff= 2 , 0
           316.9 2482.34
Permanent Ineff=
       F       F
Bank Sta=359.3,378.7
XS Rating Curve= 0 ,0
Exp/Cntr(USF)=0,0
Exp/Cntr=0.3,0.1

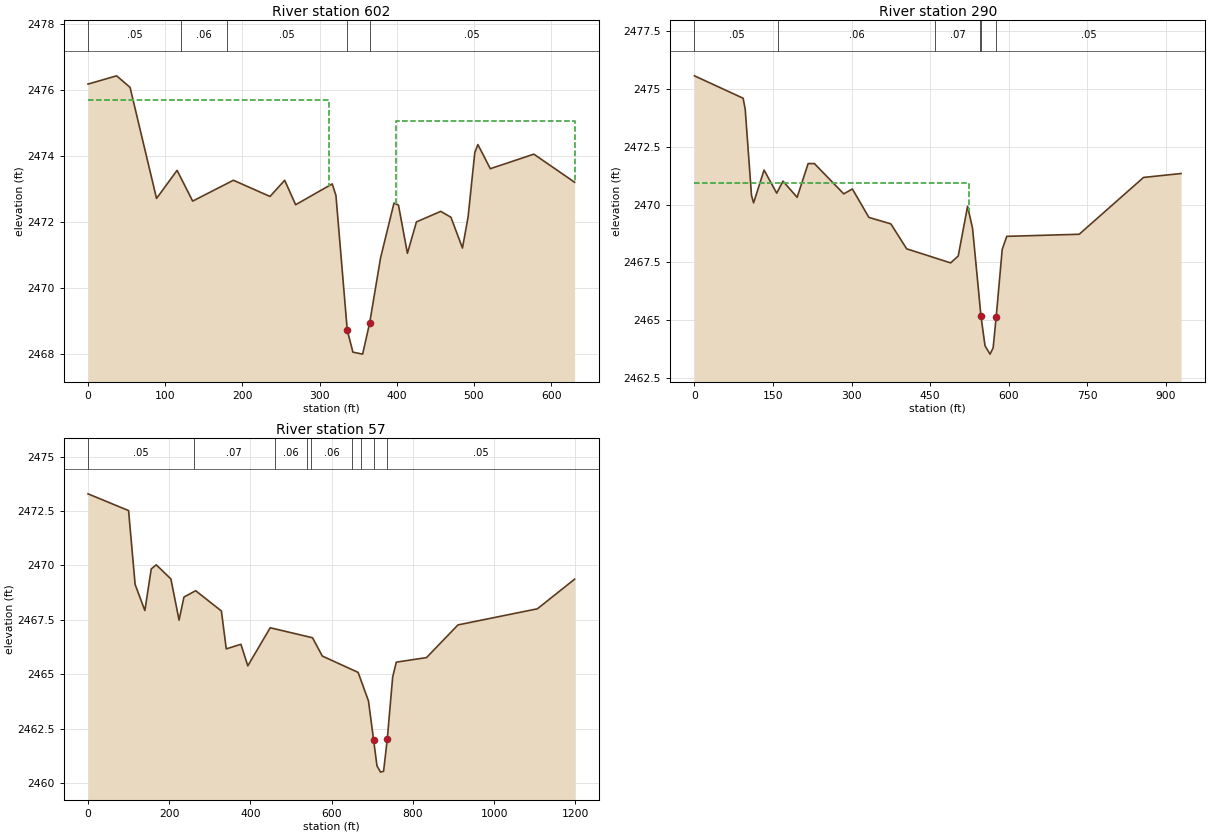
Type RM Length L Ch R = 1 ,602     ,318.9,311.9,302
XS GIS Cut Line= 3
2284043.81751578455478.2807064722284285.83383938455858.374282619
2284464.98127924455873.350942738
#Sta/Elev= 30
       0 2476.18    37.1 2476.43    54.5 2476.08    88.8 2472.72   115.4 2473.57
   135.6 2472.64   188.4 2473.27   235.8 2472.78   254.8 2473.27     269 2472.53
   316.4 2473.16   321.2 2472.81335.89642468.727   343.2 2468.07   355.8 2468.01
 364.8962468.955     379 2470.92   396.4 2472.58   402.2 2472.52   413.8 2471.06
   425.5 2472.01     457 2472.33   470.2 2472.15   485.1 2471.22   492.4 2472.16
   501.1 2474.11   505.1 2474.35   521.2 2473.62   577.6 2474.06   630.4 2473.21
#Mann= 5 ,-1,0
       0     .05       0     120     .06       0     180     .05       0
335.8964    .045       0 364.896     .05       0
#XS Ineff= 2 , 0
          312.73  2475.7  399.49         2475.07
Permanent Ineff=
       F       F
Bank Sta=335.8964,364.896
XS Rating Curve= 0 ,0
Exp/Cntr(USF)=0,0
Exp/Cntr=0.3,0.1

Type RM Length L Ch R = 1 ,290     ,232.9,232.9,232.9
XS GIS Cut Line= 4
2283980.81694075455468.2914573042283966.60859914  455963.8073709
2284112.24410063456057.9376340562284366.21820688456002.880310323
#Sta/Elev= 30
       0 2475.58    92.9 2474.61    96.9 2474.13   108.9  2470.4   112.9 2470.08
   132.9  2471.5     157  2470.5     169 2471.02     196 2470.32     217 2471.78
     229 2471.78     285 2470.47   301.5 2470.68     333 2469.45   374.9 2469.17
   405.1 2468.09   489.1 2467.48   503.6 2467.78   521.4 2469.93   530.9 2468.98
     547 2465.17   554.7 2463.89   564.3 2463.53   570.2  2463.8     576 2465.13
   587.5 2468.06   596.2 2468.63   734.5 2468.72   857.3 2471.18     929 2471.35
#Mann= 6 ,-1,0
       0     .05       0     160     .06       0     460     .07       0
  545.72     .05       0     547    .045       0     576     .05       0
#XS Ineff= 2 , 0
          523.38 2470.93
Permanent Ineff=
       F       F
Bank Sta=547,576
XS Rating Curve= 0 ,0
Exp/Cntr(USF)=0,0
Exp/Cntr=0.3,0.1

Type RM Length L Ch R = 1 ,57      ,,,
XS GIS Cut Line= 4
2283841.40481185455469.422868184  2283800.558707456129.148926679
2283899.03480411456178.6190194122284318.22506261456098.186123122
#Sta/Elev= 30
       0 2473.29    99.9 2472.52     116 2469.13     140 2467.93   155.7 2469.84
   168.1 2470.03   204.1 2469.38   224.2 2467.49   236.2 2468.55   265.1 2468.84
   328.4 2467.91   340.4 2466.17   376.5 2466.38   393.4 2465.39   448.6 2467.14
   552.8 2466.68   576.9 2465.84     665 2465.09   690.5 2463.78   703.1 2461.99
   711.4  2460.8   720.3 2460.51   727.7 2460.55   736.7 2462.01   750.1 2464.88
     759 2465.56   833.4 2465.77   910.8 2467.27  1106.3 2468.01    1198 2469.37
#Mann= 9 ,-1,0
       0     .05       0     260     .07       0     460     .06       0
     540     .07       0     550     .06       0     650     .08       0
  670.99     .05       0   703.1    .045       0   736.7     .05       0
Bank Sta=703.1,736.7
XS Rating Curve= 0 ,0
Exp/Cntr(USF)=0,0
Exp/Cntr=0.3,0.1
LCMann Table=0

Chan Stop Cuts=-1
Use User Specified Reach Order=0
Composite Channel Slope=5